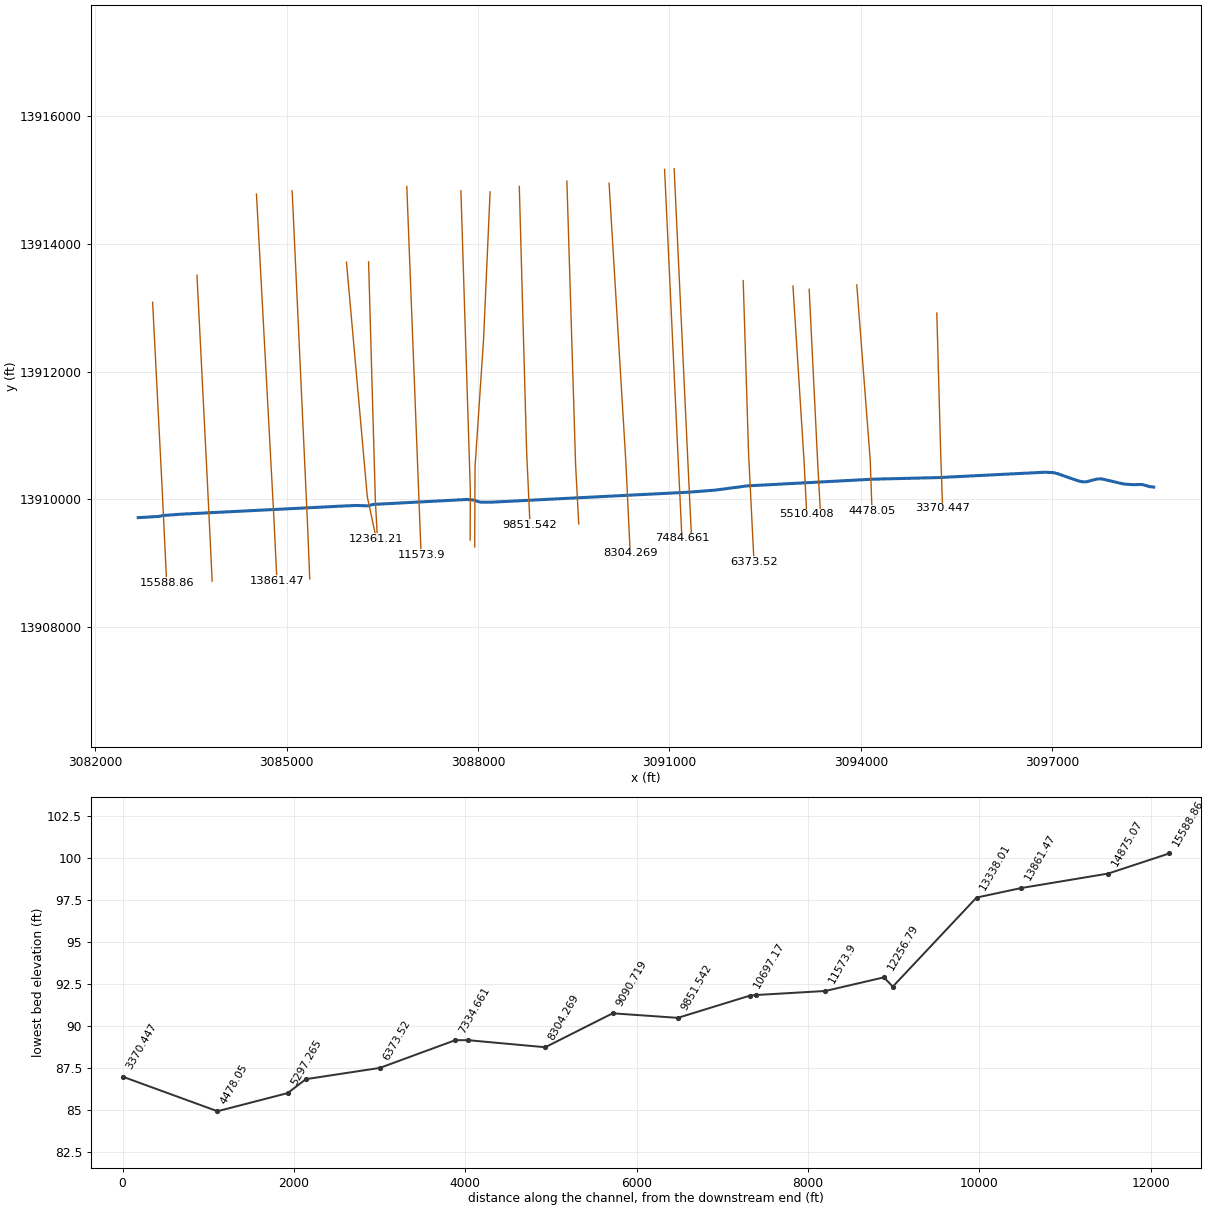
--- P147-00-00.prj (project) ---

Proj Title=P147-00-00
Current Plan=p01
Default Exp/Contr=0.3,0.1
English Units
Geom File=g01
Flow File=f01
Flow File=f02
Plan File=p01
Plan File=p02
Y Axis Title=Elevation
X Axis Title(PF)=Main Channel Distance
X Axis Title(XS)=Station
BEGIN DESCRIPTION:
HCFCD Watershed Unit ID: P
M3 Study Identifier: 2007_Effective_P
Engineer: HCFCD
Project Name: EffectiveFEMA Study for watershed Greens Bayou (P)
Study Completion Date: 6/18/2007
FEMA Case Number: [No Data]
FEMA Approval Date: [No Date in Database]
Vertical Datum: NAVD 1988
Datum Note: 2001 ADJ
HYDRAULICS
HCFCD Unit No.:  P147-00-00
Hydraulic Program Name: HEC-RAS
Hydraulic Program Version: 3.0.1
Steady Hydraulic Model: Yes
Unsteady Hydraulic Model: No
Update 1:
The effective FEMA hydraulic model for unit number P100-00-00 has been updated by FEMA LOMR 13-06-2759P with an effective date of 9/15/2014.
END DESCRIPTION:
DSS Export Rating Curves= 0
DSS Export Rating Curve Sorted= 0
DSS Export Volume Flow Curves= 0
DXF OffsetX= 0
DXF OffsetY= 0
DXF ScaleX= 1
DXF ScaleY= 10

--- P147-00-00.p01 (plan) ---

Plan Title=FEMA Effective Multi-Profile 2014
Program Version=4.10
Short Identifier=Eff+LOMR MP
Geom File=g01
Flow File=f01
Subcritical Flow
K Sum by GR= 0
Std Step Tol= 0.01
Critical Tol= 0.01
Num of Std Step Trials= 20
Max Error Tol= 0.3
Flow Tol Ratio= 0.001
Split Flow NTrial= 30
Split Flow Tol= 0.02
Split Flow Ratio= 0.02
Log Output Level= 0
Friction Slope Method= 0
Unsteady Friction Slope Method= 2
Unsteady Bridges Friction Slope Method= 1
Secant Critical Depth
Global Vel Dist= 0 , 0 , 0
Global Log Level= 0
CheckData=True
Encroach Param=-1 ,0,0, 2
BEGIN DESCRIPTION:
FEMA Effective June 2007 + LOMR 13-06-2759P
END DESCRIPTION:
Computation Interval=1HOUR
Output Interval=1HOUR
Run HTab= 0
Run UNet= 0
Run PostProcess= 0
Run WQNet= 0
UNET Theta= 1
UNET Theta Warmup= 1
UNET ZTol= 0.02
UNET ZSATol= 0.1
UNET MxIter= 20
UNET MaxInSteps= 20
UNET DtIC= 0
UNET DtMin= 0
UNET MaxCRTS= 20
UNET WFStab= 2
UNET SFStab= 1
UNET WFX= 1
UNET SFX= 1
UNET DSS MLevel= 4
UNET DZMax Abort= 100
UNET Convert EG Bridges=-1
UNET Use Existing IB Tables=-1
UNET Froude Reduction=False
UNET Froude Limit= 1
UNET Froude Power= 10
UNET Time Slicing=0,0, 5
UNET Junction Losses=0
Instantaneous Interval=1HOUR
Write IC File= 0
IC Time=0,,
Write IC File at Sim End=0
Echo Input=False
Echo Parameters=False
Echo Output=False
Write Detailed= 0
WQ AD Non Conservative
WQ ULTIMATE=-1
WQ Max Comp Step=1HOUR
WQ Output Interval=15MIN
WQ Output Selected Increments= 0
WQ Output face flow=0
WQ Output face velocity=0
WQ Output face area=0
WQ Output face dispersion=0
WQ Output cell volume=0
WQ Output cell surface area=0
WQ Output cell continuity=0
WQ Output cumulative cell continuity=0
WQ Output face conc=0
WQ Output face dconc_dx=0
WQ Output face courant=0
WQ Output face peclet=0
WQ Output face adv mass=0
WQ Output face disp mass=0
WQ Output cell mass=0
WQ Output cell source sink temp=0
WQ Output cell source sink nsm=0
WQ Output MaxMinRange=-1
WQ Daily Max Min Mean=-1
WQ Daily Range=0
WQ Daily Time=0
WQ Create Restart=0
WQ Fixed Restart=0
WQ System Summary=0
WQ Use Fixed Temperature=0
Sorting and Armoring Iterations= 10
XS Update Threshold= 0.02
Hydraulics Update Threshold= 0.02
Energy Slope Method= 1
Volume Change Method= 0
XS Weighting Method= 0
Number of US Weighted Cross Sections= 1
Number of DS Weighted Cross Sections= 1
Upstream XS Weight=0.25
Main XS Weight=0.5
Downstream XS Weight=0.25
Number of DS XS's Weighted with US Boundary= 1
Upstream Boundary Weight= 1
Weight of XSs Associated with US Boundary= 0
Number of US XS's Weighted with DS Boundary= 1
Downstream Boundary Weight= 0.5
Weight of XSs Associated with DS Boundary= 0.5
Sediment Output Level= 4
Mass or Volume Output= 0
Output Increment Type= 1
Profile and TS Output Increment= 10
XS Output Flag= 0
XS Output Increment= 10
Disregard all LS=0
Disregard all Conn=0
Disregard all Breaches=0
Disregard all Pumps=0

--- P147-00-00.p02 (plan) ---

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Plan Title=FEMA Effective Floodway 2014
Short Identifier=Eff+LOMR FW
Geom File=g01
Flow File=f02
Encroach River=P147-00-00
Encroach Reach=P147-00-00_0001
Encroach Node=15588.86
       1 3243.94 3380.83
Encroach Node=14875.07
       1 3627.63 3767.04
Encroach Node=13861.47
       1 4844.24 4987.53
Encroach Node=13338.01
       1 4940.29 5014.14
Encroach Node=12361.21
       1 4770.13  4915.3
Encroach Node=12358.21
       1 4659.07  4915.3
Encroach Node=12256.79
       1 4659.07 4804.75
Encroach Node=11573.9
       1 4916.42 4997.42
Encroach Node=10769.25
       1 4804.59 4867.81
Encroach Node=10759.25
       1 4787.99 4867.81
Encroach Node=10697.17
       1 4787.99  4860.6
Encroach Node=9851.542
       1 4874.01 4949.38
Encroach Node=9090.719
       1 4915.76 4996.47
Encroach Node=8304.269
       1 4851.77 4926.43
Encroach Node=7484.661
       1 4988.96 5105.47
Encroach Node=7389.259
       1 4988.96 5105.47
Encroach Node=7334.661
       1 4988.96 5105.47
Encroach Node=6373.52
       1 3171.96 3254.39
Encroach Node=5510.408
       1 3039.45 3132.63
Encroach Node=5484.69
       1    2841    3162
Encroach Node=5297.265
       1 2933.06 3059.78
Encroach Node=4478.05
       1 2982.67 3093.69
Encroach Node=4449.233
       1 2982.67 3093.69
Encroach Node=3370.447
       1 2516.74  2633.4
Encroach Node=2931.11
       1 2239.64 2342.39
Encroach Node=1772.284
       1   436.2     549
Encroach Node=1729.8
       1   436.2     549
Encroach Node=1572.284
       1   436.2     549
Encroach Node=950.4488
       1   568.3   663.2
Encroach Node=860.4491
       1   441.2   538.2
Encroach Node=798.9
       1     435   528.5
Encroach Node=736.9327
       1     435   528.5
Encroach Node=369.1198
       1   562.9   661.6
Encroach Node=133.9
       1  887.35  966.54

--- P147-00-00.f01 (steady flow) ---

Flow Title=FEMA Effective June 2007
Program Version=4.10
Number of Profiles= 4
Profile Names=10PCT_10yr, 2PCT_50yr, 1PCT_100yr, 0.2PCT_500yr
River Rch & RM=P147-00-00,P147-00-00_0001 ,15588.86
      33      49      57      79
River Rch & RM=P147-00-00,P147-00-00_0001 ,14875.07
      72     105     122     171
River Rch & RM=P147-00-00,P147-00-00_0001 ,13861.47
     107     156     182     254
River Rch & RM=P147-00-00,P147-00-00_0001 ,13338.01
     223     327     380     532
River Rch & RM=P147-00-00,P147-00-00_0001 ,12361.21
     326     478     555     777
River Rch & RM=P147-00-00,P147-00-00_0001 ,12256.79
     326     478     555     777
River Rch & RM=P147-00-00,P147-00-00_0001 ,11573.9
     480     704     817    1145
River Rch & RM=P147-00-00,P147-00-00_0001 ,10769.25
     519     762     885    1239
River Rch & RM=P147-00-00,P147-00-00_0001 ,10697.17
     519     762     885    1239
River Rch & RM=P147-00-00,P147-00-00_0001 ,9851.542
     554     813     944    1322
River Rch & RM=P147-00-00,P147-00-00_0001 ,9090.719
     593     870    1010    1415
River Rch & RM=P147-00-00,P147-00-00_0001 ,8304.269
     640     940    1092    1529
River Rch & RM=P147-00-00,P147-00-00_0001 ,7484.661
     781    1149    1335    1867
River Rch & RM=P147-00-00,P147-00-00_0001 ,7334.661
     781    1149    1335    1867
River Rch & RM=P147-00-00,P147-00-00_0001 ,6373.52
     811    1195    1388    1941
River Rch & RM=P147-00-00,P147-00-00_0001 ,5510.408
     849    1252    1454    2033
River Rch & RM=P147-00-00,P147-00-00_0001 ,5297.265
     849    1252    1454    2033
River Rch & RM=P147-00-00,P147-00-00_0001 ,4478.05
     892    1316    1528    2137
River Rch & RM=P147-00-00,P147-00-00_0001 ,3370.447
     892    1316    1528    2137
River Rch & RM=P147-00-00,P147-00-00_0001 ,2931.11
     910    1343    1559    2179
River Rch & RM=P147-00-00,P147-00-00_0001 ,1772.284
    1030    1522    1767    2469
Boundary for River Rch & Prof#=P147-00-00,P147-00-00_0001 , 1
Up Type= 0
Dn Type= 3
Dn Slope=0.0006
Boundary for River Rch & Prof#=P147-00-00,P147-00-00_0001 , 2
Up Type= 0
Dn Type= 3
Dn Slope=0.0006
Boundary for River Rch & Prof#=P147-00-00,P147-00-00_0001 , 3
Up Type= 0
Dn Type= 3
Dn Slope=0.0006
Boundary for River Rch & Prof#=P147-00-00,P147-00-00_0001 , 4
Up Type= 0
Dn Type= 3
Dn Slope=0.0006
DSS Import GetInterval= 0
DSS Import GetPeak= 0
DSS Import FillOption= 0

--- P147-00-00.f02 (steady flow) ---

Flow Title=Floodway
Program Version=4.10
Number of Profiles= 2
Profile Names=1PCT_100yr, 1PCTFloodway_100yrFW
River Rch & RM=P147-00-00,P147-00-00_0001 ,15588.86
      57      57
River Rch & RM=P147-00-00,P147-00-00_0001 ,14875.07
     122     122
River Rch & RM=P147-00-00,P147-00-00_0001 ,13861.47
     182     182
River Rch & RM=P147-00-00,P147-00-00_0001 ,13338.01
     380     380
River Rch & RM=P147-00-00,P147-00-00_0001 ,12361.21
     555     555
River Rch & RM=P147-00-00,P147-00-00_0001 ,12256.79
     555     555
River Rch & RM=P147-00-00,P147-00-00_0001 ,11573.9
     817     817
River Rch & RM=P147-00-00,P147-00-00_0001 ,10769.25
     885     885
River Rch & RM=P147-00-00,P147-00-00_0001 ,10697.17
     885     885
River Rch & RM=P147-00-00,P147-00-00_0001 ,9851.542
     944     944
River Rch & RM=P147-00-00,P147-00-00_0001 ,9090.719
    1010    1010
River Rch & RM=P147-00-00,P147-00-00_0001 ,8304.269
    1092    1092
River Rch & RM=P147-00-00,P147-00-00_0001 ,7484.661
    1335    1335
River Rch & RM=P147-00-00,P147-00-00_0001 ,7334.661
    1335    1335
River Rch & RM=P147-00-00,P147-00-00_0001 ,6373.52
    1388    1388
River Rch & RM=P147-00-00,P147-00-00_0001 ,5510.408
    1454    1454
River Rch & RM=P147-00-00,P147-00-00_0001 ,5297.265
    1454    1454
River Rch & RM=P147-00-00,P147-00-00_0001 ,4478.05
    1528    1528
River Rch & RM=P147-00-00,P147-00-00_0001 ,3370.447
    1528    1528
River Rch & RM=P147-00-00,P147-00-00_0001 ,2931.11
    1559    1559
River Rch & RM=P147-00-00,P147-00-00_0001 ,1772.284
    1767    1767
Boundary for River Rch & Prof#=P147-00-00,P147-00-00_0001 , 1
Up Type= 0
Dn Type= 3
Dn Slope=0.0006
Boundary for River Rch & Prof#=P147-00-00,P147-00-00_0001 , 2
Up Type= 0
Dn Type= 3
Dn Slope=0.0006
DSS Import GetInterval= 0
DSS Import GetPeak= 0
DSS Import FillOption= 0

--- P147-00-00.g01 (geometry) ---

Geom Title=P147-00-00
Program Version=4.10

River Reach=P147-00-00      ,P147-00-00_0001
Reach XY= 30
 3082670.998940913909710.0034443 3082992.502234913909729.0004536
 3083053.999487213909743.0007537 3083355.751836513909764.9961165
 3085880.747442613909891.9968467 3086084.752940113909900.9997815
 3086275.249606413909895.0034024 3086350.247487913909916.9987652
 3087821.997497113909995.0028743 3087912.002894613909988.9982931
  3088040.24870113909952.0032884 3088220.251621913909953.0026302
 3091300.501038813910109.0029744 3091721.749868213910142.0002837
  3092220.00379313910208.0031045 3094192.252473113910312.9999417
  3095213.24583813910338.0021883 3096885.503320213910422.0030046
  3097011.75044313910415.9980953  3097083.74997113910399.9991116
 3097408.497024913910285.9993396 3097471.002149213910272.9987094
 3097534.998084213910271.9990395 3097701.500375913910314.9989535
   3097774.7449813910317.9973071 3098123.748875213910237.0030465
 3098272.245297413910227.0004418 3098407.495026913910230.0069975
   3098531.7513413910196.0018162 3098591.225302513910188.9650848

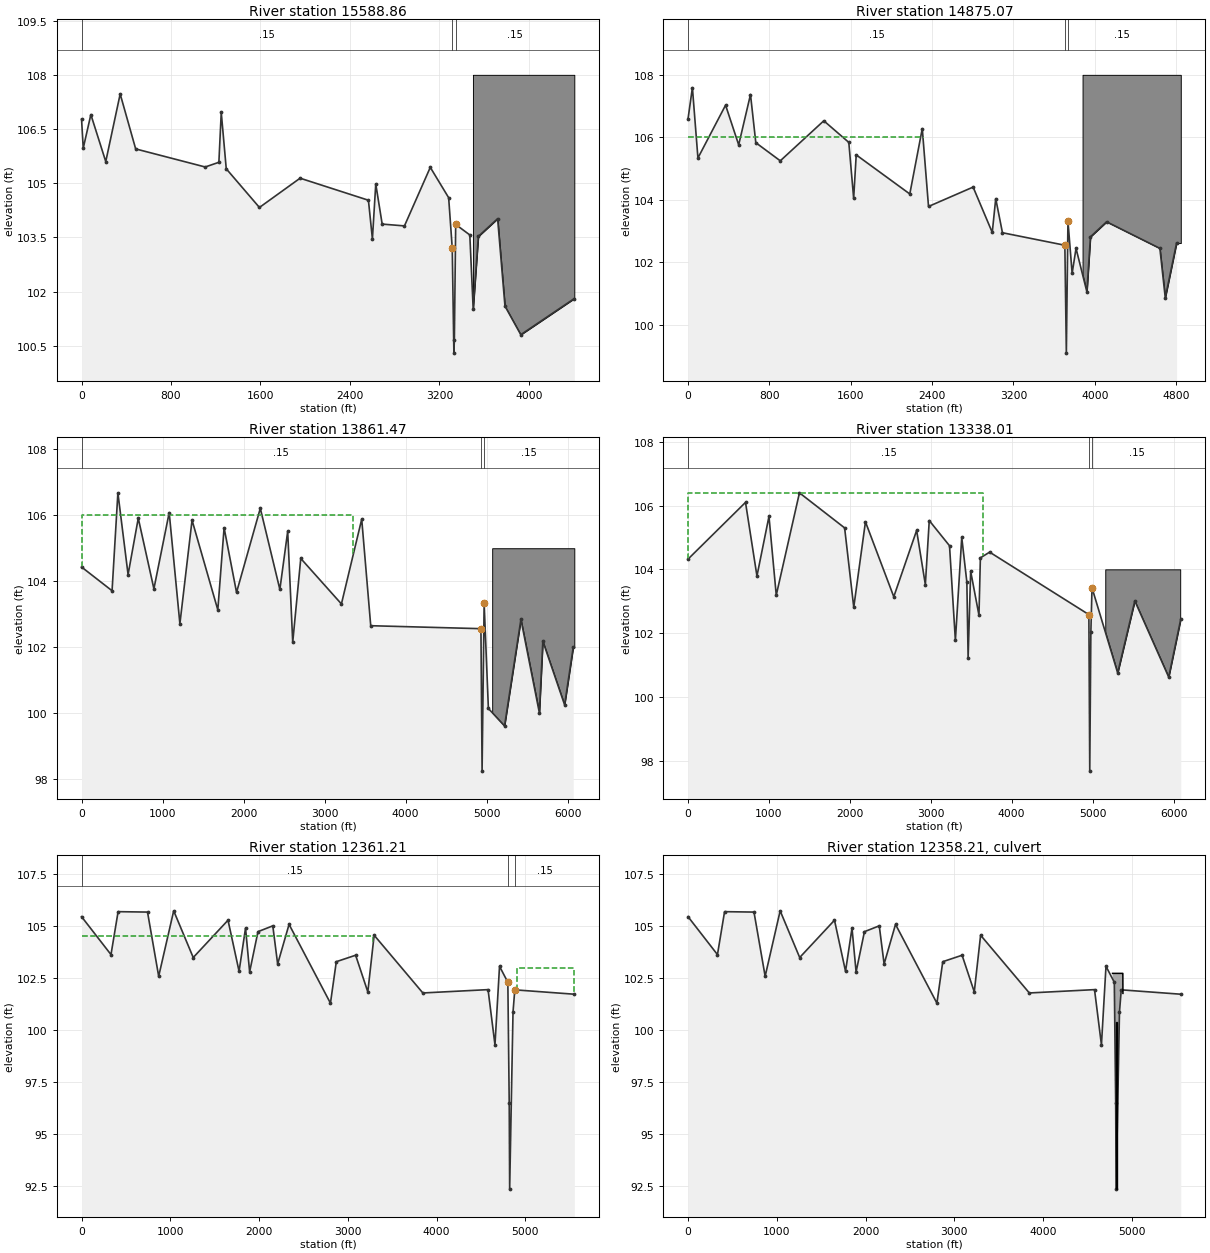
Type RM Length L Ch R = 1 ,15588.86,713.79,713.79,713.79
BEGIN DESCRIPTION:
15455
END DESCRIPTION:
XS GIS Cut Line= 4
     3082896.463    13913087.624     3083040.895     13910261.62
     3083088.969    13909262.776     3083116.702    13908686.566
#Sta/Elev= 30
       0  106.77   15.05  105.97   83.24   106.9  216.47   105.6   345.4  107.47
  483.97  105.95 1105.85  105.45 1228.13  105.58 1249.25  106.96    1294   105.4
 1590.64  104.33 1954.32  105.14 2565.41  104.53 2601.01  103.46 2631.05  104.98
 2688.37  103.87 2887.64  103.82  3118.6  105.44  3282.9   104.6 3314.85  103.21
 3329.69   100.3 3333.92  100.67 3345.84  103.86 3472.06  103.57 3502.09  101.53
 3548.51  103.53 3720.73  104.02 3786.47   101.6 3928.02  100.81 4406.57  101.81
#Mann= 3 , 0 , 0
       0     .15       0 3314.85     .04       0 3345.84     .15       0
#Block Obstruct= 1 ,-1
    3500 4406.57     108
Bank Sta=3314.85,3345.84
XS Rating Curve= 0 ,0
Exp/Cntr=0.3,0.1

Type RM Length L Ch R = 1 ,14875.07,1013.02,1013.6,1014.03
BEGIN DESCRIPTION:
14741
END DESCRIPTION:
XS GIS Cut Line= 4
     3083591.748    13913511.579      3083753.86    13910295.935
     3083801.934    13909297.091     3083830.001     13908713.95
#Sta/Elev= 30
       0  106.59   43.08  107.59   97.45  105.34  369.27  107.03  498.12  105.76
  614.28  107.37  666.47  105.83  907.08  105.25 1334.98  106.53 1580.84  105.84
 1628.64  104.05 1653.67  105.44 2180.49  104.19 2303.21  106.28 2364.58  103.79
 2803.01  104.41 2991.25  102.96 3025.42  104.04  3091.6  102.95 3705.09  102.55
 3719.73    99.1 3735.54  103.32 3776.61  101.65 3814.98  102.45 3921.69  101.06
  3956.8  102.82 4115.43   103.3 4639.28  102.45 4692.37  100.87 4803.54  102.62
#Mann= 3 , 0 , 0
       0     .15       0 3705.09     .04       0 3735.54     .15       0
#XS Ineff= 1 ,-1
       0 2310.23     106
Permanent Ineff=
       T
#Block Obstruct= 1 ,-1
    3879 4844.83     108
Bank Sta=3705.09,3735.54
XS Rating Curve= 0 ,0
Exp/Cntr=0.3,0.1

Type RM Length L Ch R = 1 ,13861.47,524.04,523.46,523.89
BEGIN DESCRIPTION:
13728
END DESCRIPTION:
XS GIS Cut Line= 4
     3084524.448    13914783.441     3084794.669    13909764.593
     3084814.976    13909346.949     3084845.321    13908722.845
#Sta/Elev= 30
       0  104.43  376.64  103.71  448.51  106.68  574.27   104.2  700.11  105.91
  893.09  103.77 1081.85  106.08 1213.87  102.71 1364.02  105.85 1682.03  103.13
 1759.56  105.62 1913.23  103.66 2206.47  106.21 2448.04  103.75 2544.63  105.51
 2606.81  102.15 2706.06  104.69  3207.9  103.31 3458.44  105.88 3569.68  102.65
 4930.04  102.56 4944.25   98.24 4969.59  103.33 5022.08  100.14  5221.4   99.61
 5423.73  102.84 5651.41  100.01 5694.38  102.18 5962.94  100.25  6069.1  101.99
#Mann= 3 , 0 , 0
       0     .15       0 4930.04     .04       0 4969.59     .15       0
#XS Ineff= 1 ,-1
       0 3349.84     106
Permanent Ineff=
       T
#Block Obstruct= 1 ,-1
 5068.97 6082.76     105
Bank Sta=4930.04,4969.59
XS Rating Curve= 0 ,0
Exp/Cntr=0.3,0.1

Type RM Length L Ch R = 1 ,13338.01,972.92,976.8,978.64
BEGIN DESCRIPTION:
13204
END DESCRIPTION:
XS GIS Cut Line= 5
     3085084.067    13914834.316     3085321.228     13909695.98
     3085334.466    13909372.223     3085359.877    13908750.781
     3085359.877    13908750.771
#Sta/Elev= 30
       0  104.32  710.44   106.1  851.88  103.79 1000.38  105.66 1090.48  103.19
 1377.14   106.4 1935.39   105.3 2048.25  102.81 2192.75  105.49 2542.89  103.14
 2825.32  105.22 2933.13  103.52 2981.34  105.53 3231.79  104.74 3304.24  101.77
 3382.96     105 3445.93   103.6 3461.67  101.22 3493.03  103.94 3595.71  102.56
 3613.16  104.36 3727.55  104.54 4953.87  102.58 4964.89   97.67 4978.61  102.03
 4992.79  103.42 5309.93  100.75 5521.77  103.01 5940.45  100.62  6089.8  102.44
#Mann= 3 , 0 , 0
       0     .15       0 4953.87     .04       0 4992.79     .15       0
#XS Ineff= 1 ,-1
       0    3644   106.4
Permanent Ineff=
       T
#Block Obstruct= 2 ,-1
                         5156.52 6082.76     104
Bank Sta=4953.87,4992.79
XS Rating Curve= 0 ,0
Exp/Cntr=0.5,0.3

Type RM Length L Ch R = 1 ,12361.21,107.44,104.42,101.44
BEGIN DESCRIPTION:
12227
END DESCRIPTION:
XS GIS Cut Line= 4
     3085935.935    13913715.537     3086262.393    13910036.906
     3086393.433    13909422.957     3086402.835    13909375.526
#Sta/Elev= 30
       0  105.44  331.66  103.62  411.79  105.68  743.23  105.66  869.01  102.58
 1038.07  105.72 1258.13  103.48 1650.12  105.27 1774.63  102.82 1847.51  104.89
 1893.65  102.79 1987.62  104.72 2154.56     105 2209.26  103.17 2337.84  105.07
 2804.19  101.29 2870.09  103.28 3087.84  103.59 3225.16  101.83 3296.37  104.55
  3845.2  101.78 4579.89  101.94 4657.76   99.29 4709.03  103.06 4802.84  102.29
 4818.29    96.5 4823.27   92.37    4861  100.86 4881.06  101.93 5551.64  101.72
#Mann= 3 , 0 , 0
       0     .15       0 4802.84     .04       0 4881.06     .15       0
#XS Ineff= 2 ,-1
       0 3287.13   104.5 4910.89    6000     103
Permanent Ineff=
       T       F
Bank Sta=4802.84,4881.06
XS Rating Curve= 0 ,0
Skew Angle= 35
Exp/Cntr=0.5,0.3

Type RM Length L Ch R = 2 ,12358.21,,,
BEGIN DESCRIPTION:
Veterans Memorial
END DESCRIPTION:
Bridge Culvert--1,0,-1,-1, 0
Deck Dist Width WeirC Skew NumUp NumDn MinLoCord MaxHiCord MaxSubmerge Is_Ogee
3,100,2.6,35, 8, 10, , , 0.95, 0, 0,0,,
 4782.86    4790    4815    4836    4872    4891    4899    4900
  102.72  102.72  102.72  102.72  102.72  102.72  102.72  101.76
                                                                
 4753.26    4762    4768    4769    4772    4779    4783    4789    4795 4805.51
  100.28     102     102     102     102     102     102     102     102     101
                                                                                
Pier Skew= 35
BR Coef=-1 , 1 , 0 ,, 0 ,,,0.8,-1,0.6,0,
WSPro=,,,, 1 ,,,, 0 ,,,, 0 ,,,,-1 ,-1 ,-1 , 0 , 0 , 0 , 0 , 0
Culvert=2,8,8,100,0.013,0.4,1,8,1,92.38,4826.9,92.48,4783.76,Culvert #1  , 0 ,3
Culvert Bottom n=0.013
BC Design=,, 0 ,, 0 ,,,,,,
BC HTab HWMax=105.87
BC Use User HTab Curves=0
BC User HTab FreeFlow(D)= 0

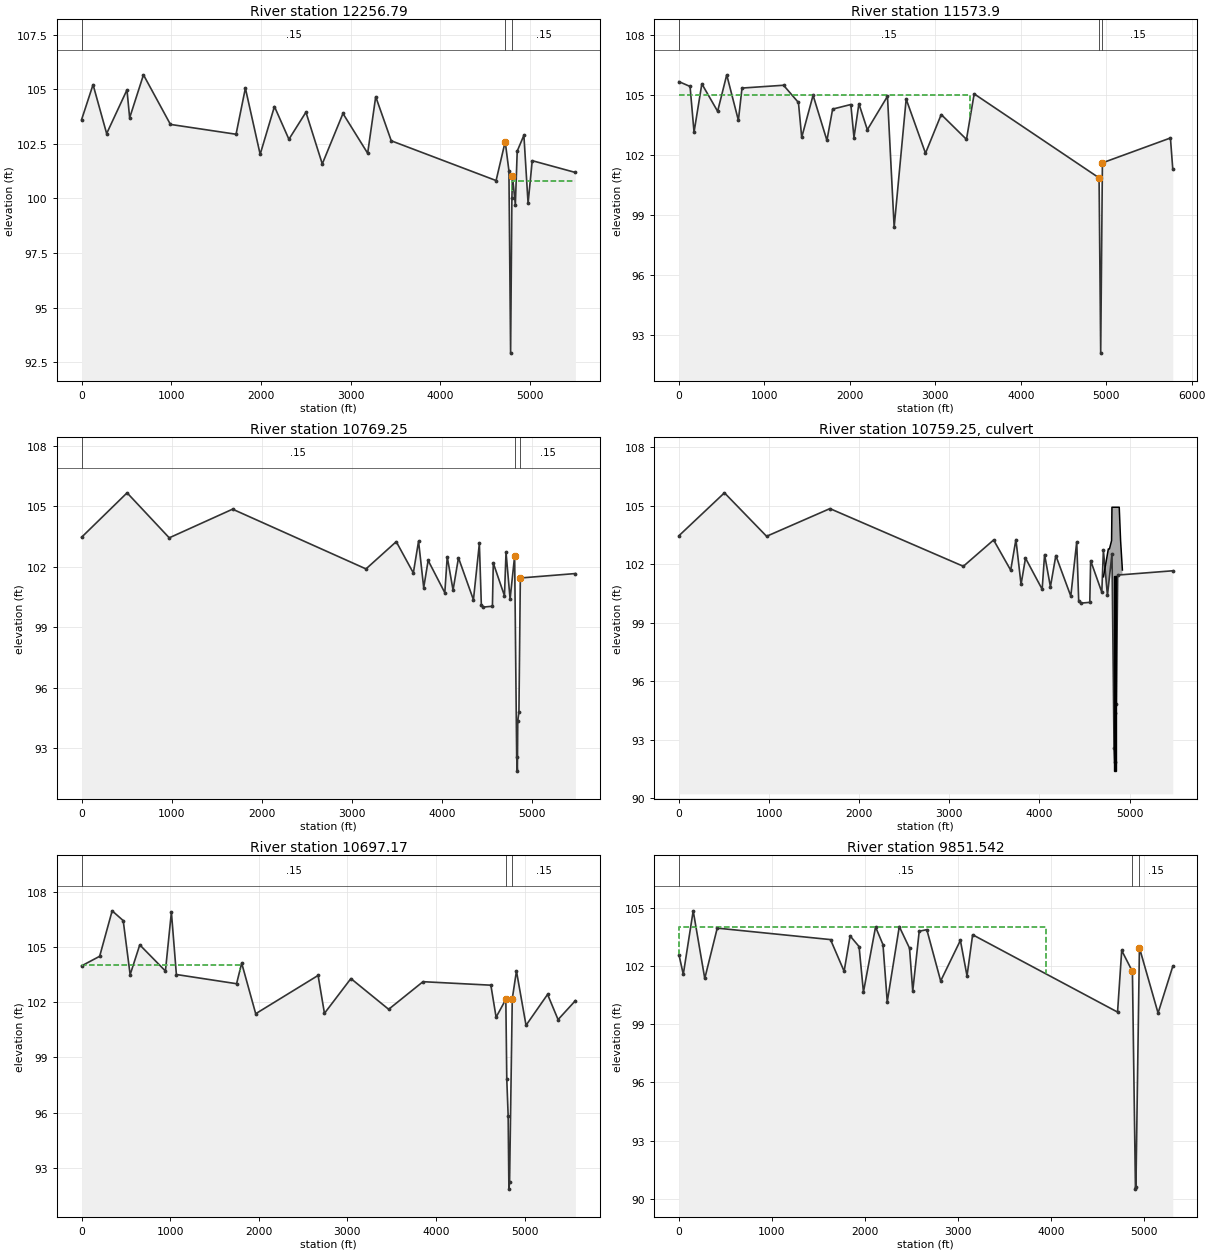
Type RM Length L Ch R = 1 ,12256.79,683.2,682.89,682.62
BEGIN DESCRIPTION:
12123
END DESCRIPTION:
XS GIS Cut Line= 4
     3086282.433    13913720.176     3086388.469    13909984.205
     3086418.183    13909434.248     3086422.181    13909348.187
#Sta/Elev= 30
       0  103.61  127.67  105.21  279.27  102.97  505.81  104.97  535.82  103.69
  689.85  105.66  990.55  103.39  1722.4  102.94 1826.34  105.05 1991.08  102.02
 2150.36  104.21 2311.77  102.71 2501.62  103.95 2683.79  101.58 2914.47  103.89
 3189.83  102.07 3279.63  104.66 3453.02  102.64 4622.13  100.82 4723.58   102.6
 4765.09  101.27 4783.93   92.92 4798.26     100 4804.75  101.02 4836.71   99.72
  4857.7  102.17 4931.99  102.89 4978.73   99.78 5025.04  101.73 5506.45  101.19
#Mann= 3 , 0 , 0
       0     .15       0 4723.58     .04       0 4804.75     .15       0
#XS Ineff= 2 , 0
       0 4763.76  101.21 4800.32       0  100.82
Permanent Ineff=
       F       F
Bank Sta=4723.58,4804.75
XS Rating Curve= 0 ,0
Skew Angle= 35
Exp/Cntr=0.5,0.3

Type RM Length L Ch R = 1 ,11573.9 ,806.02,804.65,803.37
BEGIN DESCRIPTION:
11440
END DESCRIPTION:
XS GIS Cut Line= 6
     3086881.632    13914902.153     3086881.633    13914902.149
     3087045.507    13910679.342     3087053.658    13910469.985
      3087092.56    13909470.741     3087105.914    13909127.697
#Sta/Elev= 30
       0  105.65  130.02  105.41  176.41  103.13  267.71  105.54  452.49  104.17
  558.95  105.99  695.41  103.72   737.7  105.33  1223.8  105.47  1398.2  104.61
 1436.42  102.87 1569.58  104.97 1731.56  102.72 1798.33  104.28 2011.35  104.51
 2048.16  102.86 2105.81  104.55 2204.48  103.25 2440.25  104.92 2518.33   98.39
 2658.89  104.78 2885.13  102.08 3069.24  104.01 3364.68  102.77 3454.75  105.04
 4916.42  100.85  4935.5   92.11 4955.57   101.6 5751.62  102.84 5778.81   101.3
#Mann= 3 , 0 , 0
       0     .15       0 4916.42     .04       0 4955.57     .15       0
#XS Ineff= 1 ,-1
       0 3405.94     105
Permanent Ineff=
       T
Bank Sta=4916.42,4955.57
XS Rating Curve= 0 ,0
Exp/Cntr=0.5,0.3

Type RM Length L Ch R = 1 ,10769.25,72.5,72.08,72
BEGIN DESCRIPTION:
10635
END DESCRIPTION:
XS GIS Cut Line= 4
 3087729.542043513914834.3146213     3087877.606    13910136.802
     3087875.439    13909501.668     3087874.948    13909357.862
#Sta/Elev= 30
       0  103.46  504.57  105.66  972.34  103.43 1675.15  104.85 3155.36  101.89
 3491.05  103.24 3680.65  101.69 3738.49  103.26 3795.76  100.96 3844.88  102.31
 4029.82  100.71 4056.64  102.49 4121.36  100.84 4181.39  102.44  4347.5  100.36
  4413.3  103.15 4435.05  100.12 4458.41     100 4558.15  100.04 4567.73  102.18
 4691.65  100.56 4709.06  102.71 4754.18   100.4 4804.59  102.53 4827.36   92.57
 4834.99   91.87 4839.39   94.36 4852.25    94.8 4867.81  101.44 5478.79  101.66
#Mann= 3 , 0 , 0
       0     .15       0 4804.59     .04       0 4867.81     .15       0
#XS Ineff= 1 ,-1
       0 4709.06     102
Permanent Ineff=
       T
Bank Sta=4804.59,4867.81
XS Rating Curve= 0 ,0
Exp/Cntr=0.5,0.3

Type RM Length L Ch R = 2 ,10759.25,,,
BEGIN DESCRIPTION:
Walters
END DESCRIPTION:
Bridge Culvert--1,0,-1,-1, 0
Deck Dist Width WeirC Skew NumUp NumDn MinLoCord MaxHiCord MaxSubmerge Is_Ogee
10,60,2.6,0, 9, 9, , , 0.95, 0, 0,0,,
 4709.73    4764    4776    4800    4804    4850    4885    4900    4920
  101.35  102.78  102.78  103.21  104.92  104.92  104.92  103.21   101.7
                                                                        
  4707.9    4764    4776    4790    4800    4821    4860    4880    4891
  101.03  102.78  102.78  103.21  104.92  104.92  104.92  103.21  102.84
                                                                        
BR Coef=-1 , 1 , 0 ,, 0 ,,,0.8,-1,0.6,0,
WSPro=,,,, 1 ,,,, 0 ,,,, 0 ,,,,-1 ,-1 ,-1 , 0 , 0 , 0 , 0 , 0
Culvert=2,10,10,60,0.013,0.4,1,8,1,91.38,4833,91.38,4818.09,Culvert #1  , 0 ,10
Culvert Bottom n=0.013
Culvert=2,10,10,60,0.013,0.4,1,8,1,91.38,4846.57,91.38,4831.66,Culvert #2  , 0 ,10
Culvert Bottom n=0.013
BC Design=,, 0 ,, 0 ,,,,,,
BC HTab HWMax=105.66
BC Use User HTab Curves=0
BC User HTab FreeFlow(D)= 0

Type RM Length L Ch R = 1 ,10697.17,844.07,845.628,847.61
BEGIN DESCRIPTION:
10563
END DESCRIPTION:
XS GIS Cut Line= 6
 3088187.412880113914817.3552872     3088085.385    13912508.798
     3087951.222    13910501.415     3087950.308    13910272.567
     3087947.226    13909501.423     3087946.226    13909250.957
#Sta/Elev= 30
       0  103.97  203.76  104.49  344.79  106.96  469.48  106.43  547.89  103.49
  656.43  105.11  946.05  103.69 1013.35  106.89  1069.7   103.5 1749.04     103
 1806.76  104.12 1964.93  101.37 2669.13  103.45 2740.89  101.39 3039.35  103.28
 3465.56  101.61 3853.13  103.11 4619.09  102.92 4678.13  101.18 4787.99  102.15
 4798.63   97.82 4814.11   95.84 4822.67   91.84 4830.19   92.22  4860.6  102.18
  4907.8  103.69    5016  100.74 5259.14  102.42  5377.6  101.05 5573.14  102.08
#Mann= 3 , 0 , 0
       0     .15       0 4787.99     .04       0  4860.6     .15       0
#XS Ineff= 1 ,-1
       0 1782.18     104
Permanent Ineff=
       T
Bank Sta=4787.99,4860.6
XS Rating Curve= 0 ,0
Exp/Cntr=0.5,0.3

Type RM Length L Ch R = 1 ,9851.542,760.58,760.82,761.08
BEGIN DESCRIPTION:
9718
END DESCRIPTION:
XS GIS Cut Line= 5
 3088645.282946513914902.1509357     3088645.283    13914902.149
     3088760.147    13910748.004     3088771.736    13910497.578
     3088813.399     13909597.29
#Sta/Elev= 30
       0  102.57   46.48  101.56  153.02  104.83  277.34  101.35  411.48  103.94
 1628.94  103.35 1775.28  101.72 1839.57  103.54 1936.02  102.99 1982.91  100.65
 2113.22     104 2192.99  103.09 2238.71  100.15  2368.3  104.02  2478.1  102.91
 2512.85   100.7 2582.38  103.78 2664.24  103.86 2813.04  101.22 3024.98  103.31
 3096.26  101.48 3156.59   103.6 4714.33   99.62    4759  102.79 4874.01  101.71
  4906.7   90.51 4911.76   90.62 4949.38  102.93  5149.8   99.57 5307.68  101.97
#Mann= 3 , 0 , 0
       0     .15       0 4874.01     .04       0 4949.38     .15       0
#XS Ineff= 1 ,-1
       0    3940     104
Permanent Ineff=
       T
Bank Sta=4874.01,4949.38
XS Rating Curve= 0 ,0
Exp/Cntr=0.3,0.1

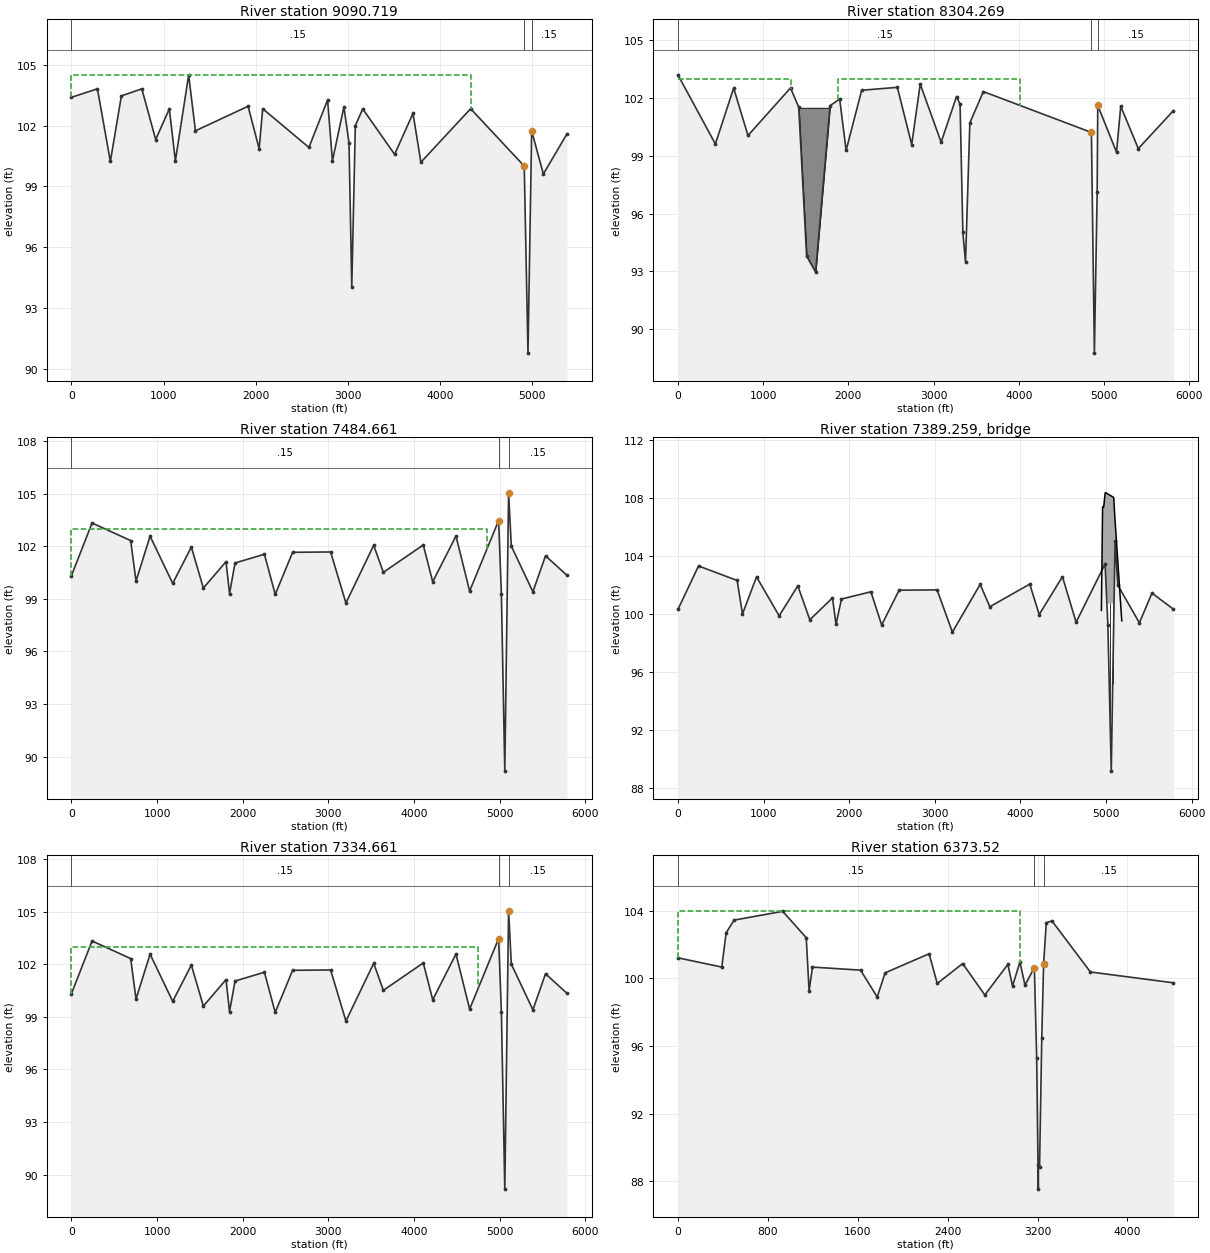
Type RM Length L Ch R = 1 ,9090.719,786.66,786.45,786.27
BEGIN DESCRIPTION:
8956
END DESCRIPTION:
XS GIS Cut Line= 3
  3089391.44301213914986.9396103     3089528.326    13910532.579
      3089577.32    13909610.623
#Sta/Elev= 30
       0  103.39  282.07  103.81  422.43  100.23  542.16  103.46  763.99  103.81
  914.64  101.31 1062.44  102.82 1128.32  100.26 1272.54  104.49 1346.18  101.74
 1917.85  102.95  2037.9  100.85 2076.33  102.83 2578.16  100.92 2780.74  103.26
 2833.28  100.26 2957.96  102.92 3013.36  101.14 3043.38   94.06  3082.1     102
 3162.58  102.82  3508.6  100.58 3708.12   102.6 3793.73  100.19  4333.8  102.83
 4915.76     100 4956.46   90.78 4996.47  101.74 5123.28   99.61 5379.72  101.59
#Mann= 3 , 0 , 0
       0     .15       0 4915.76     .04       0 4996.47     .15       0
#XS Ineff= 1 ,-1
       0 4336.63   104.5
Permanent Ineff=
       T
Bank Sta=4915.76,4996.47
XS Rating Curve= 0 ,0
Exp/Cntr=0.3,0.1

Type RM Length L Ch R = 1 ,8304.269,900.44,900.495,900.71
BEGIN DESCRIPTION:
8170
END DESCRIPTION:
XS GIS Cut Line= 5
     3090052.811    13914953.023     3090316.416    13910574.452
     3090363.987    13909575.584     3090384.342    13909148.194
     3090384.342    13909148.184
#Sta/Elev= 30
       0  103.21  439.59   99.62  654.21  102.52  822.28  100.06 1321.53  102.53
 1417.59  101.53 1510.21    93.8 1615.65   92.97 1785.64  101.61 1898.17  101.95
 1973.73   99.29 2156.39  102.41 2574.88  102.56 2743.32   99.59 2843.02  102.73
 3088.61   99.71 3268.93  102.08 3310.78  101.69 3343.43   95.03 3374.74    93.5
 3425.44  100.71 3583.72  102.34 4851.77  100.22 4886.83   88.76 4919.42   97.14
 4926.43  101.62 5146.81   99.19 5195.93  101.58  5402.1   99.38 5814.38  101.35
#Mann= 3 , 0 , 0
       0     .15       0 4851.77     .04       0 4926.43     .15       0
#XS Ineff= 2 ,-1
       0  1326.7     103 1881.19  4019.8     103
Permanent Ineff=
       T       T
#Block Obstruct= 1 ,-1
    1346 1881.19   101.5
Bank Sta=4851.77,4926.43
XS Rating Curve= 0 ,0
Exp/Cntr=0.5,0.3

Type RM Length L Ch R = 1 ,7484.661,150,150,150
XS GIS Cut Line= 4
 3090923.118919613915170.4695575  3091136.54139313910614.2788667
 3091184.111507813909615.4055364 3091194.869360313909389.5122874
#Sta/Elev= 30
       0  100.32  240.83  103.32  691.87  102.32  754.31  100.01  918.41  102.57
 1182.57   99.88 1400.44  101.95 1540.61   99.61 1805.46  101.12 1846.41    99.3
 1910.57  101.04 2253.88  101.54 2379.91   99.25 2583.18  101.65 3026.94  101.67
 3205.69   98.76 3529.99  102.05  3642.9  100.51 4109.17  102.07 4219.32   99.97
    4491  102.58 4650.52   99.44 4988.96  103.46 5021.36   99.27 5061.18   89.18
 5105.47  105.04 5137.43     102 5389.45    99.4  5536.6  101.45 5787.33  100.34
#Mann= 3 , 0 , 0
       0     .15       0 4988.96     .04       0 5105.47     .15       0
#XS Ineff= 1 ,-1
       0 4851.49     103
Permanent Ineff=
       T
Bank Sta=4988.96,5105.47
XS Rating Curve= 0 ,0
Skew Angle= 20
Exp/Cntr=0.5,0.3

Type RM Length L Ch R = 3 ,7389.259,,,
BEGIN DESCRIPTION:
TC Jester
END DESCRIPTION:
Bridge Culvert--1,0,-1,-1, 0
Deck Dist Width WeirC Skew NumUp NumDn MinLoCord MaxHiCord MaxSubmerge Is_Ogee
14.515,105.4,2.6,20, 8, 8, , , 0.95, 0, 0,0,,
    4946    4960    4972    4990    5000    5090    5100 5183.95
  100.26   107.4  107.36  108.36  108.36  108.04  106.97   99.54
     100     100  100.74  100.74  100.74  100.74  100.74    99.4
    4946    4960    4972    4990    5000    5090    5100 5183.95
  100.26   107.4  107.36  108.36  108.36  108.04  106.97   99.54
     100     100  100.74  100.74  100.74  100.74  100.74    99.4
Pier Skew= 20
Pier Skew, UpSta & Num, DnSta & Num=  ,5047, 2 ,5047, 2 , 0 , 0 , 0 ,,
     1.5     1.5
    94.9  100.74
     1.5     1.5
    94.9  100.74
Pier Skew, UpSta & Num, DnSta & Num=  ,5078, 2 ,5078, 2 , 0 , 0 , 0 ,,
     1.5     1.5
   91.46  100.74
     1.5     1.5
   91.46  100.74
BR Coef=-1 , 1 , 1 ,1.05, 0 ,,,0.8,-1,1.2,0,
WSPro=,,,, 1 ,,,, 0 ,,,, 0 ,,,,-1 ,-1 ,-1 , 0 , 0 , 0 , 0 , 0
BC Design=,, 0 ,, 0 ,,,,,,
BC HTab HWMax=105.04
BC Use User HTab Curves=0
BC User HTab FreeFlow(D)= 0

Type RM Length L Ch R = 1 ,7334.661,880.3,880.25,879.45
XS GIS Cut Line= 4
 3091073.205233513915179.3766919 3091286.627378913910623.1915786
 3091334.197165613909624.3234976 3091344.955018113909398.4305767
#Sta/Elev= 30
       0  100.32  240.83  103.32  691.87  102.32  754.31  100.01  918.41  102.57
 1182.57   99.88 1400.44  101.95 1540.61   99.61 1805.46  101.12 1846.41    99.3
 1910.57  101.04 2253.88  101.54 2379.91   99.25 2583.18  101.65 3026.94  101.67
 3205.69   98.76 3529.99  102.05  3642.9  100.51 4109.17  102.07 4219.32   99.97
    4491  102.58 4650.52   99.44 4988.96  103.46 5021.36   99.27 5061.18   89.18
 5105.47  105.04 5137.43     102 5389.45    99.4  5536.6  101.45 5787.33  100.34
#Mann= 3 , 0 , 0
       0     .15       0 4988.96     .04       0 5105.47     .15       0
#XS Ineff= 1 ,-1
       0  4752.4     103
Permanent Ineff=
       T
Bank Sta=4988.96,5105.47
XS Rating Curve= 0 ,0
Skew Angle= 20
Exp/Cntr=0.5,0.3

Type RM Length L Ch R = 1 ,6373.52 ,863.11,863.11,863.11
BEGIN DESCRIPTION:
6240
END DESCRIPTION:
XS GIS Cut Line= 4
     3092155.625    13913426.788     3092239.686    13910722.595
     3092289.522    13909723.838     3092324.606    13909020.719
#Sta/Elev= 30
       0  101.22   390.6  100.67  429.08   102.7  499.92  103.45   932.8  103.97
 1141.97  102.41 1167.35   99.26 1197.37  100.67 1625.64  100.49 1773.37    98.9
    1844  100.33 2235.41  101.46 2307.79    99.7 2533.66  100.88 2731.19   99.02
 2936.03  100.83 2977.56   99.55 3043.51  100.97 3088.57    99.6 3171.96  100.64
 3192.48    95.3 3207.05   87.53 3208.72   88.98 3217.98   88.81 3237.57   96.45
 3254.39  100.88 3277.91   103.3 3328.87   103.4 3670.57  100.38 4409.49   99.74
#Mann= 3 , 0 , 0
       0     .15       0 3171.96     .04       0 3254.39     .15       0
#XS Ineff= 1 ,-1
       0  3045.2     104
Permanent Ineff=
       T
Bank Sta=3171.96,3254.39
XS Rating Curve= 0 ,0
Exp/Cntr=0.5,0.3

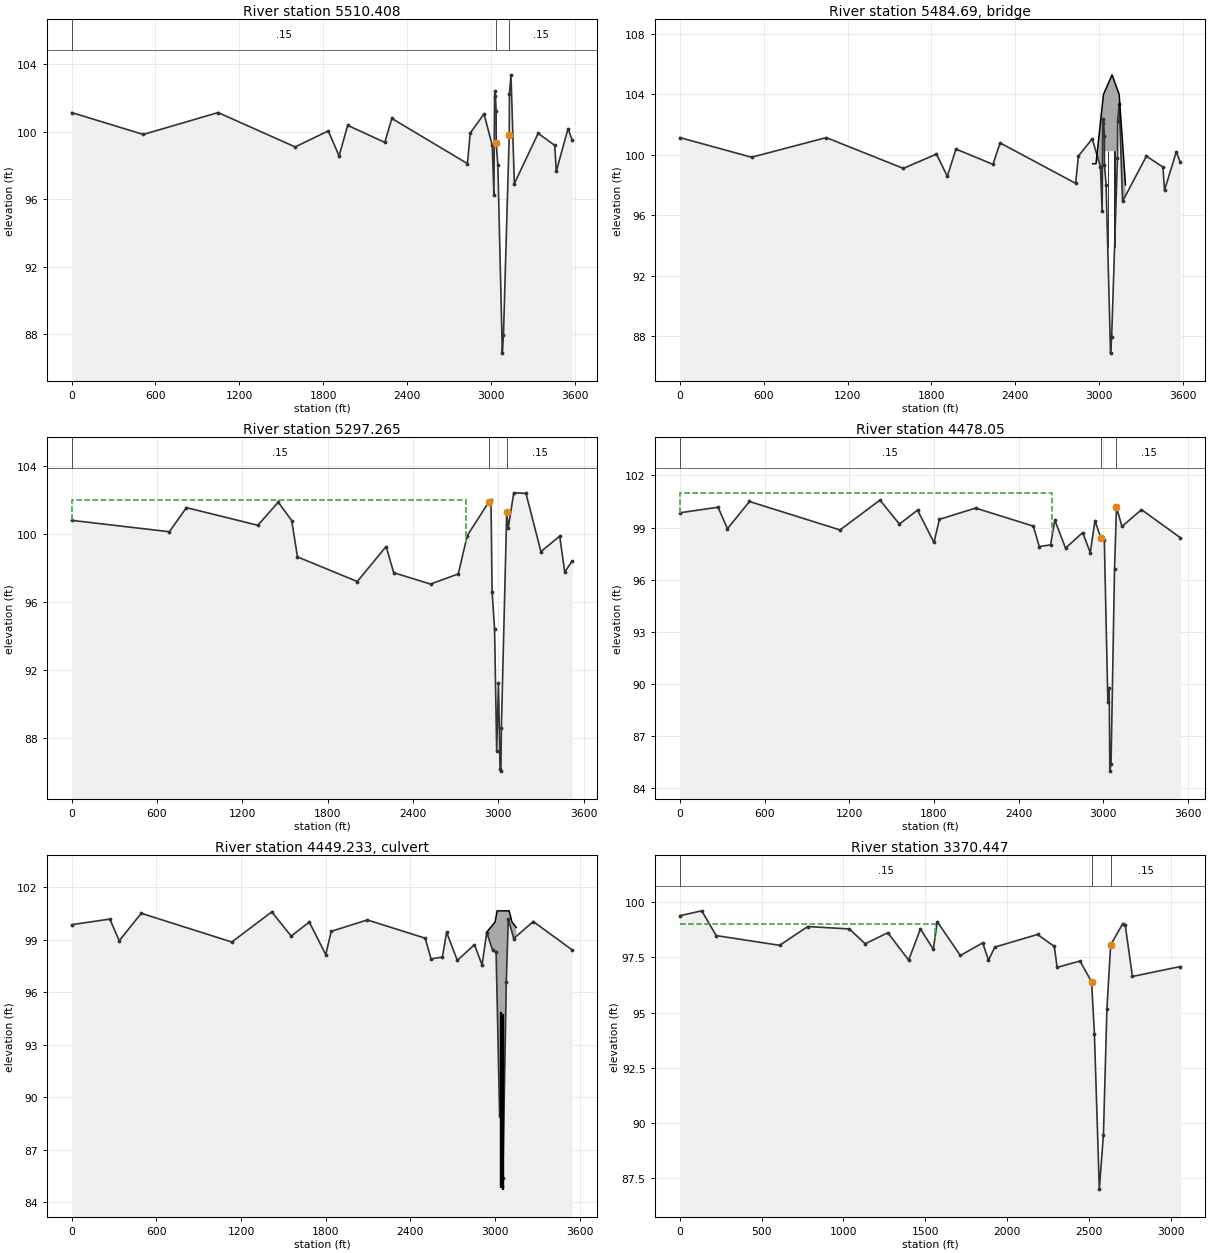
Type RM Length L Ch R = 1 ,5510.408,213.4,213.14,213
XS GIS Cut Line= 3
     3092935.701    13913341.997     3093111.967    13910560.344
     3093151.633    13909765.407
#Sta/Elev= 30
       0  101.14  513.02   99.84 1047.85  101.14 1599.68    99.1 1836.94  100.05
 1914.47   98.57 1976.18  100.38 2241.48   99.37 2292.25  100.79 2833.37   98.11
  2852.9   99.92 2952.24  101.06 3010.97   99.19 3022.87   96.25 3027.41   102.1
 3032.33   102.4 3039.07  101.24 3039.45   99.31 3051.16   98.03 3083.05   86.86
 3091.24   87.94 3132.63   99.81 3134.16  102.26 3145.13  103.38 3169.05   96.92
 3339.76   99.91 3458.41   99.19 3469.39   97.65 3553.64  100.19 3583.16    99.5
#Mann= 3 , 0 , 0
       0     .15       0 3039.45     .04       0 3132.63     .15       0
#XS Ineff= 1 ,-1
       0 3032.33     101
Permanent Ineff=
       T
#Block Obstruct= 1 ,-1
    3020    3025    96.5
Bank Sta=3039.45,3132.63
XS Rating Curve= 0 ,0
Exp/Cntr=0.5,0.3

Type RM Length L Ch R = 3 ,5484.69 ,,,
BEGIN DESCRIPTION:
Adel
END DESCRIPTION:
Bridge Culvert--1,0,-1,-1, 0
Deck Dist Width WeirC Skew NumUp NumDn MinLoCord MaxHiCord MaxSubmerge Is_Ogee
25.72,38.6,2.6,0, 6, 7, , , 0.95, 0, 0,0,,
 2955.72 2979.02 3032.38    3094    3145  3190.2
   99.41   99.41     104   105.3     104      98
                  100.24  100.24  100.24
 2932.43    2940    2967    3010    3054    3084  3112.8
   100.2     101     104   105.3   105.3     104   100.2
          100.24  100.24  100.24  100.24  100.24
Pier Skew, UpSta & Num, DnSta & Num=  ,3063.2, 2 ,2977.52, 2 , 0 , 0 , 0 ,,
     1.5     1.5
   91.06  100.24
     1.5     1.5
   91.06  100.24
Pier Skew, UpSta & Num, DnSta & Num=  ,3112, 2 ,3038.27, 2 , 0 , 0 , 0 ,,
     1.5     1.5
   89.81  100.24
     1.5     1.5
   89.81  100.24
BR Coef=-1 , 1 , 1 ,1.05, 0 ,,,0.8,-1,1.2,0,
WSPro=,,,, 1 ,,,, 0 ,,,, 0 ,,,,-1 ,-1 ,-1 , 0 , 0 , 0 , 0 , 0
BC Design=,, 0 ,, 0 ,,,,,,
BC HTab HWMax=103.38
BC Use User HTab Curves=0
BC User HTab FreeFlow(D)= 0

Type RM Length L Ch R = 1 ,5297.265,817.22,819.22,819.22
BEGIN DESCRIPTION:
5163
END DESCRIPTION:
XS GIS Cut Line= 3
     3093190.073    13913291.122     3093326.399    13910510.019
     3093367.688    13909775.555
#Sta/Elev= 30
       0  100.79  686.95  100.12  807.09  101.54 1309.29   100.5 1452.86  101.86
 1547.31  100.78 1588.03   98.64 2008.53   97.19 2211.58   99.25  2264.8   97.71
 2523.92   97.04 2719.19   97.64 2781.98   99.89 2933.06  101.86 2949.08  101.96
 2957.01   96.58 2974.27   94.38 2989.19   87.23 3001.64   91.22 3012.76   86.13
 3018.78   86.03  3022.1   88.57 3059.78  101.28 3070.47  100.34  3109.2  102.41
 3195.11  102.38 3300.27   98.95 3432.38   99.86 3467.59   97.75 3520.07   98.39
#Mann= 3 , 0 , 0
       0     .15       0 2933.06     .04       0 3059.78     .15       0
#XS Ineff= 1 ,-1
       0    2772     102
Permanent Ineff=
       T
Bank Sta=2933.06,3059.78
XS Rating Curve= 0 ,0
Exp/Cntr=0.5,0.3

Type RM Length L Ch R = 1 ,4478.05 ,1110.5,1107.6,1098.45
BEGIN DESCRIPTION:
4344.15
END DESCRIPTION:
XS GIS Cut Line= 3
     3093936.233    13913358.955     3094147.408    13910611.408
      3094174.98    13909821.052
#Sta/Elev= 30
       0   99.85  270.38  100.17  337.01   98.93  492.78   100.5 1134.64   98.86
 1417.77  100.58 1555.34    99.2 1683.73     100 1800.38   98.14 1838.89   99.47
 2095.12  100.12 2504.48   99.08 2546.44    97.9 2626.64      98 2656.71   99.42
 2732.64   97.81 2854.05   98.71 2907.91   97.55 2941.23    99.4 2982.67   98.39
 3007.39   98.27  3032.5   88.96 3042.04   89.74 3046.49   84.95 3055.06   85.38
 3079.79    96.6 3093.69  100.17 3132.29   99.06 3270.83  100.03 3546.49   98.41
#Mann= 3 , 0 , 0
       0     .15       0 2982.67     .04       0 3093.69     .15       0
#XS Ineff= 1 ,-1
       0    2640     101
Permanent Ineff=
       T
Bank Sta=2982.67,3093.69
XS Rating Curve= 0 ,0
Exp/Cntr=0.5,0.3

Type RM Length L Ch R = 2 ,4449.233,,,
BEGIN DESCRIPTION:
Trickey
END DESCRIPTION:
Bridge Culvert--1,0,-1,-1, 0
Deck Dist Width WeirC Skew NumUp NumDn MinLoCord MaxHiCord MaxSubmerge Is_Ogee
28.817,42,2.6,0, 7, 7, , , 0.95, 0, 0,0,,
 2940.93    3000    3015    3098    3100    3120 3150.15
   99.42     100  100.64  100.64  100.64     100   99.69
                                                        
 2455.55 2506.05    2580    2600    2650    2690    2707
   95.97  100.64  100.64  100.64  100.64  100.64   97.64
                                                        
BR Coef=-1 , 1 , 0 ,, 0 ,,,0.8,-1,0.6,0,
WSPro=,,,, 1 ,,,, 0 ,,,, 0 ,,,,-1 ,-1 ,-1 , 0 , 0 , 0 , 0 , 0
Culvert=2,10,10,42,0.013,0.2,1,59,1,84.86,3039,86,2560,Culvert #1  , 0 ,28.817
Culvert Bottom n=0.013
Culvert=2,10,10,42,0.013,0.2,1,59,1,84.76,3053,85.81,2575,Culvert #2  , 0 ,28.817
Culvert Bottom n=0.013
BC Design=,, 0 ,, 0 ,,,,,,
BC HTab HWMax=100.58
BC Use User HTab Curves=0
BC User HTab FreeFlow(D)= 0

Type RM Length L Ch R = 1 ,3370.447,439.34,439.34,439.34
BEGIN DESCRIPTION:
3236.55
END DESCRIPTION:
XS GIS Cut Line= 3
     3095191.137    13912918.043     3095252.702    13910696.895
      3095281.91    13909859.668
#Sta/Elev= 30
       0   99.38  133.58    99.6  221.76   98.48  609.44   98.04  781.94   98.89
 1035.82   98.78 1132.87   98.11 1271.25   98.61 1398.43   97.37 1470.48   98.78
 1549.26   97.86 1573.38   99.11 1714.38   97.58 1851.18   98.15 1886.37   97.37
 1925.62   97.96 2186.16   98.53  2288.9   97.99 2306.13   97.04 2445.96   97.33
 2516.74   96.39 2534.09   94.05  2564.1   87.01 2589.29   89.48 2610.37   95.15
  2633.4   98.06 2707.46   99.02 2722.17   98.97 2766.45   96.63 3059.74   97.08
#Mann= 3 , 0 , 0
       0     .15       0 2516.74     .04       0  2633.4     .15       0
#XS Ineff= 1 ,-1
       0  1559.4      99
Permanent Ineff=
       T
Bank Sta=2516.74,2633.4
XS Rating Curve= 0 ,0
Exp/Cntr=0.5,0.3