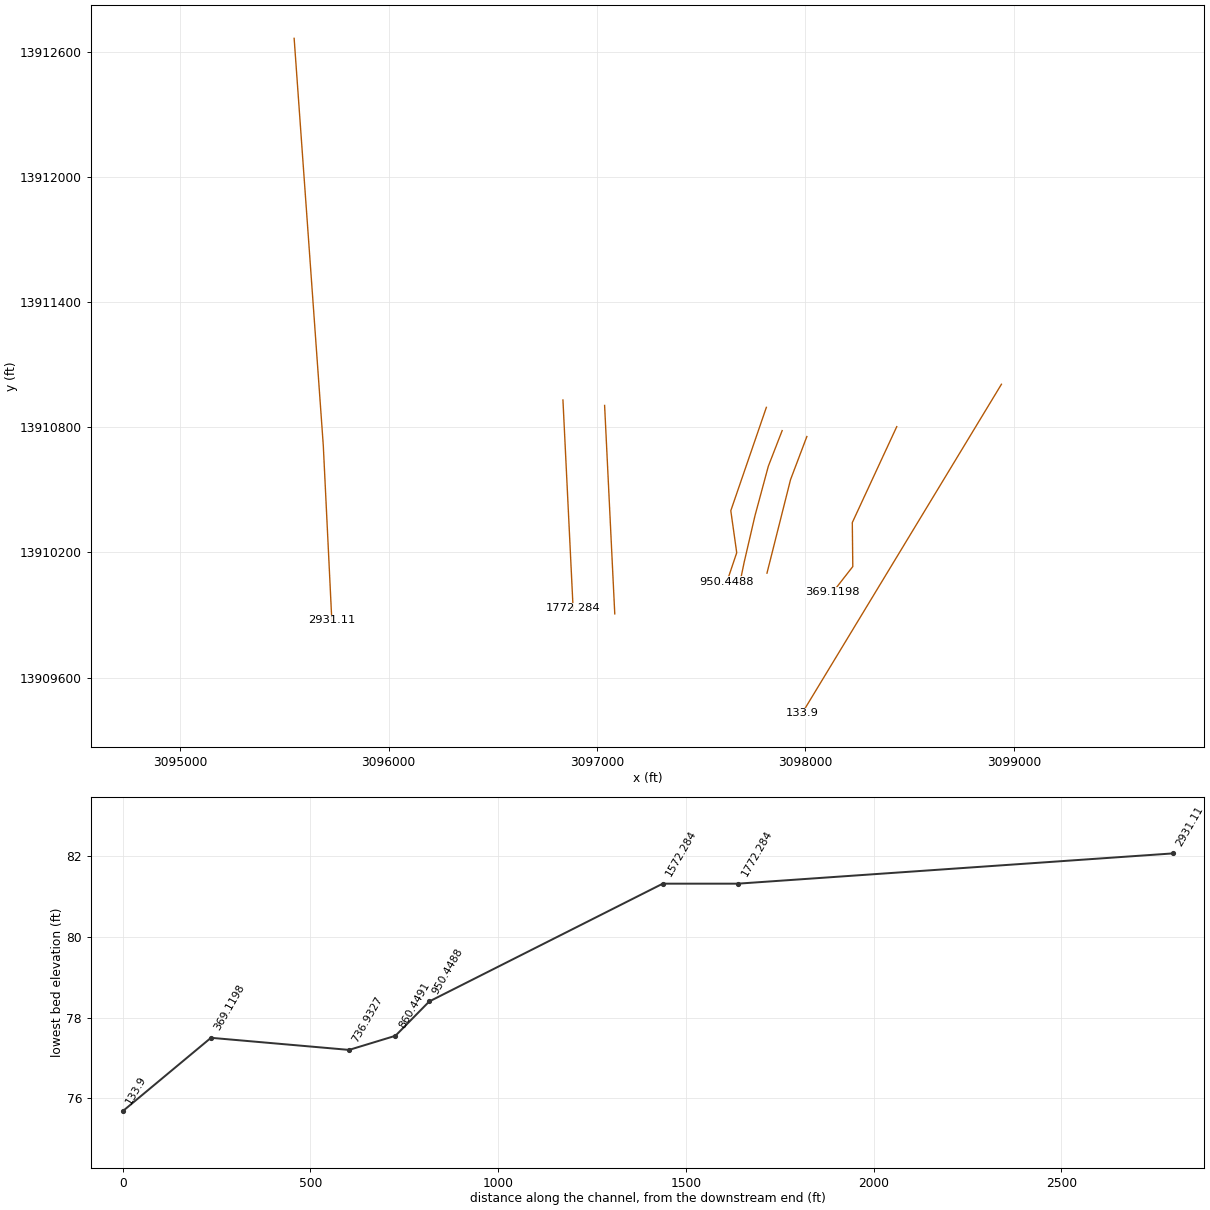
HEC-RAS study P147-00-00.prj: P147-00-00

--- P147-00-00.g01 (geometry) --- (continued)

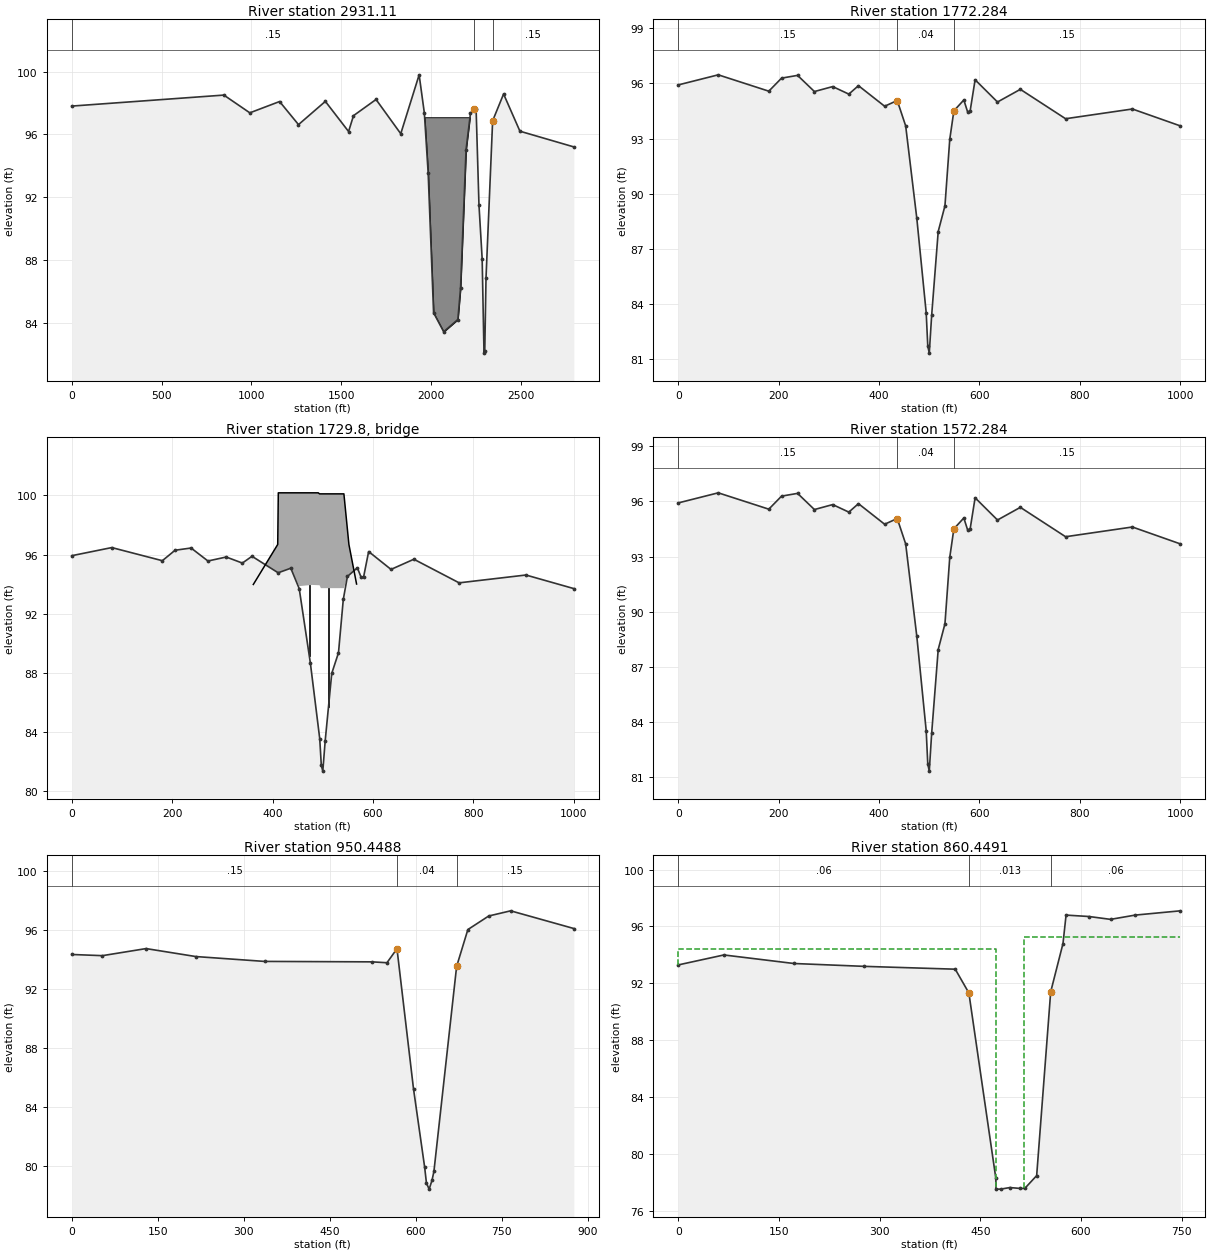
Type RM Length L Ch R = 1 ,2931.11 ,1158.826,1158.826,1158.826
BEGIN DESCRIPTION:
2784
END DESCRIPTION:
XS GIS Cut Line= 3
     3095547.259     13912663.67     3095686.998    13910713.679
     3095727.926    13909875.276
#Sta/Elev= 30
       0    97.8  846.58    98.5  991.01   97.37 1156.63   98.09  1261.9   96.62
 1411.36    98.1 1540.68   96.18 1568.01   97.19 1693.47   98.22 1831.03   96.04
 1933.32   99.79 1962.36   97.36  1983.7   93.51 2013.74   84.64    2070   83.43
  2148.9   84.21 2163.92   86.21 2194.61   95.03 2218.94   97.33 2239.64   97.63
 2250.39   97.61 2266.32   91.51 2284.07   88.08 2294.39   82.07 2298.57   82.18
 2305.55   86.86 2342.39   96.86 2403.33   98.57 2494.31    96.2 2794.39    95.2
#Mann= 3 , 0 , 0
       0     .15       0 2239.64     .04       0 2342.39     .15       0
#Block Obstruct= 1 ,-1
 1957.49 2219.88   97.09
Bank Sta=2239.64,2342.39
XS Rating Curve= 0 ,0
Exp/Cntr=0.5,0.3

Type RM Length L Ch R = 1 ,1772.284,200,200,200
BEGIN DESCRIPTION:
1638
END DESCRIPTION:
XS GIS Cut Line= 2
     3096836.616    13910930.589     3096885.374    13909931.779
#Sta/Elev= 30
       0   95.92   79.68   96.47  180.39   95.58  205.78   96.29  237.67   96.44
  271.23   95.56  307.65   95.83  339.78   95.42  358.96   95.88  411.08   94.76
   436.2   95.07     453   93.69   475.2   88.65  493.84   83.53  497.02   81.71
     500   81.32  504.73   83.37  517.79   87.94  531.22   89.34  540.81   92.96
     549   94.51  568.82    95.1  576.27   94.46  581.32   94.49  591.29    96.2
  635.87   94.99   681.4   95.68  771.51   94.08  904.54   94.61    1000   93.69
#Mann= 3 , 0 , 0
       0     .15       0   436.2     .04       0     549     .15       0
Bank Sta=436.2,549
XS Rating Curve= 0 ,0
Exp/Cntr=0.5,0.3

Type RM Length L Ch R = 3 ,1729.8  ,,,
BEGIN DESCRIPTION:
Gears-Spears Rd
END DESCRIPTION:
Bridge Culvert--1,0,-1,-1, 0
Deck Dist Width WeirC Skew NumUp NumDn MinLoCord MaxHiCord MaxSubmerge Is_Ogee
42.48,36.8,2.6,0, 10, 10, , , 0.95, 0, 0,0,,
  361.58  410.19  411.36  478.46  490.88  493.46  496.14     542     552  567.24
   93.97   96.68  100.18  100.18  100.18  100.11  100.11  100.11   96.68      94
   93.72   93.93   93.72   93.94   93.92   93.92   93.72   93.72   93.72   93.72
  361.58  410.19  411.36  478.46  490.88  493.46  496.14     542     552  567.24
   93.97   96.68  100.18  100.18  100.18  100.11  100.11  100.11   96.68      94
   93.72   93.93   93.72   93.94   93.92   93.92   93.72   93.72   93.72   93.72
Pier Skew, UpSta & Num, DnSta & Num=  ,473, 2 ,473, 2 , 0 , 0 , 0 ,,
     1.2     1.2
   85.27   93.94
     1.2     1.2
   85.27   93.94
Pier Skew, UpSta & Num, DnSta & Num=  ,511.24, 2 ,511.24, 2 , 0 , 0 , 0 ,,
     1.2     1.2
   86.56   93.94
     1.2     1.2
   86.56   93.94
BR Coef=-1 , 1 , 1 ,1.05, 0 ,,,0.8,-1,1.2,0,
WSPro=,,,, 1 ,,,, 0 ,,,, 0 ,,,,-1 ,-1 ,-1 , 0 , 0 , 0 , 0 , 0
BC Design=,, 0 ,, 0 ,,,,,,
BC HTab HWMax=96.47
BC Use User HTab Curves=0
BC User HTab FreeFlow(D)= 0

Type RM Length L Ch R = 1 ,1572.284,622,622,622
XS GIS Cut Line= 2
  3097036.46660113910904.4938375 3097085.224377513909905.6838272
#Sta/Elev= 30
       0   95.92   79.68   96.47  180.39   95.58  205.78   96.29  237.67   96.44
  271.23   95.56  307.65   95.83  339.78   95.42  358.96   95.88  411.08   94.76
   436.2   95.07     453   93.69   475.2   88.65  493.84   83.53  497.02   81.71
     500   81.32  504.73   83.37  517.79   87.94  531.22   89.34  540.81   92.96
     549   94.51  568.82    95.1  576.27   94.46  581.32   94.49  591.29    96.2
  635.87   94.99   681.4   95.68  771.51   94.08  904.54   94.61    1000   93.69
#Mann= 3 , 0 , 0
       0     .15       0   436.2     .04       0     549     .15       0
Bank Sta=436.2,549
XS Rating Curve= 0 ,0
Exp/Cntr=0.5,0.3

Type RM Length L Ch R = 1 ,950.4488,115.7,90,66.5
BEGIN DESCRIPTION:
EHRA Add'l X-Sect (April 2011)
2001 LiDAR used for Overbanks
EHRA Survey Data used for Channel
END DESCRIPTION:
XS GIS Cut Line= 4
 3097812.358752613910895.2920945  3097641.77443213910400.1237194
 3097670.205152113910198.7394519 3097622.709594513910058.1526013
#Sta/Elev= 19
       0   94.31   53.38   94.23  129.57   94.71  216.28   94.17  336.18   93.84
  523.73   93.81  549.62   93.75   567.1    94.7   595.9    85.2   615.3    79.9
   618.5    78.8   623.2    78.4   628.2      79   631.5    79.6   671.1    93.5
   690.7      96  727.11   96.92  765.31   97.27   875.5   96.07
#Mann= 3 , 0 , 0
       0     .15       0   567.1     .04       0   671.1     .15       0
Bank Sta=567.1,671.1
XS Rating Curve= 0 ,0
Exp/Cntr=0.3,0.1

Type RM Length L Ch R = 1 ,860.4491,123.6,123.5,126.7
BEGIN DESCRIPTION:
EHRA Add'l X-Sect (April 2011)
EHRA Survey Data used for Overbanks
EHRA Survey Data used for Channel
END DESCRIPTION:
XS GIS Cut Line= 5
 3097888.174006213910783.9384408 3097821.835659313910613.3541201
 3097757.866539113910376.4314526 3097706.159059413910154.3160439
 3097687.581263113910064.7110839
#Sta/Elev= 20
       0    93.3      68      94   172.3    93.4   276.5    93.2   412.7      93
     433   91.33   473.2    78.3   473.3   77.55   480.4   77.55     494   77.66
   509.3    77.6   516.3    77.6     534    78.5   554.9   91.41   573.2    94.8
   577.8    96.8   612.1    96.7   644.1    96.5   680.7    96.8     748    97.1
#Mann= 3 ,-1 , 0
       0     .06       0     433    .013       0   554.9     .06       0
#XS Ineff= 2 , 0
       0   473.5    94.4   515.7       0   95.27
Permanent Ineff=
       F       F
Bank Sta=433,554.9
XS Rating Curve= 0 ,0
Exp/Cntr=0.5,0.3

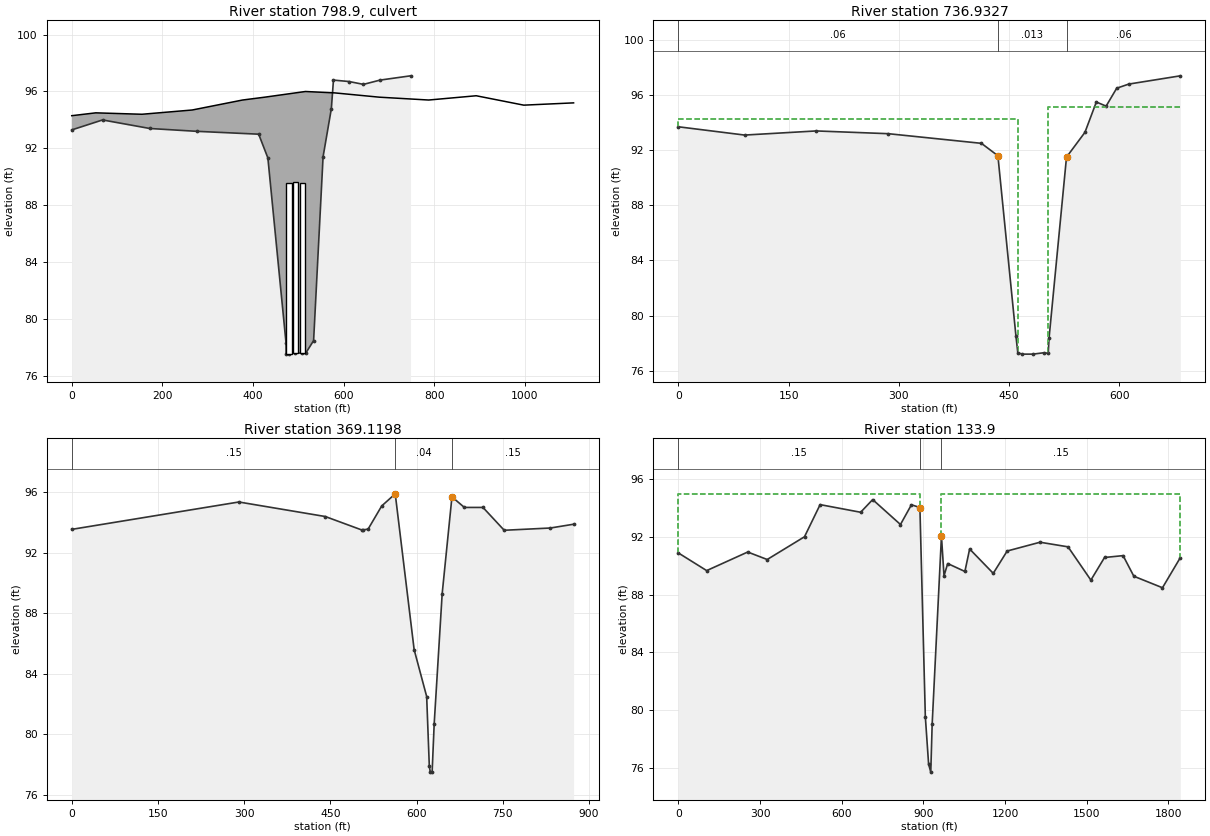
Type RM Length L Ch R = 2 ,798.9   ,,,
BEGIN DESCRIPTION:
Ella Boulevard Culvert Crossing
END DESCRIPTION:
Bridge Culvert--1,0,-1,-1, 0
Deck Dist Width WeirC Skew NumUp NumDn MinLoCord MaxHiCord MaxSubmerge Is_Ogee
0.5,122.9,2.6,0, 13, 13, 92, , 0.95, 0, 0,0,,
       0      53     155     266     377     426     516     581     679     788
     893     998    1108
    94.3    94.5    94.4    94.7    95.4    95.6      96    95.9    95.6    95.4
    95.7   95.04    95.2
                                                                                
                        
       0      53     155     266     377     426     516     581     679     788
     893     998    1108
    94.3    94.5    94.4    94.7    95.4    95.6      96    95.9    95.6    95.4
    95.7   95.04    95.2
                                                                                
                        
BR Coef=-1 , 0 , 0 ,, 0 ,,,0.8,-1,,0,
WSPro=,,,, 1 ,,,, 0 ,,,, 0 ,,,,-1 ,-1 ,-1 , 0 , 0 , 0 , 0 , 0
Culvert=2,12,12,122.9,0.015,0.5,1,10,1,77.55,480,77.19,467.5,Culvert #1  , 0 ,0.5
Culvert Bottom n=0.015
Culvert=2,12,12,122.9,0.015,0.5,1,10,1,77.66,494.3,77.23,482.3,Culvert #2  , 0 ,0.5
Culvert Bottom n=0.015
Culvert=2,12,12,122.9,0.015,0.5,1,10,1,77.6,509.2,77.26,497.2,Culvert #3  , 0 ,0.5
Culvert Bottom n=0.015
BR U #Sta/Elev= 20
       0    93.3      68      94   172.3    93.4   276.5    93.2   412.7      93
     433   91.33   473.2    78.3   473.3   77.55   480.4   77.55     494   77.66
   509.3    77.6   516.3    77.6     534    78.5   554.9   91.41   573.2    94.8
   577.8    96.8   612.1    96.7   644.1    96.5   680.7    96.8     748    97.1
BR U #Mann= 3
       0     .06     433    .013   554.9     .06
BR U Banks=433,554.9
BR D #Sta/Elev= 20
       0    93.7      90    93.1   187.5    93.4   285.5    93.2   412.3    92.5
   434.7    91.6   459.3    78.5   461.8    77.3   467.8    77.2   482.4    77.2
   497.3    77.3   503.2   77.26   504.4    78.4   528.1    91.5   553.2    93.3
   568.7    95.5     582    95.2   596.4    96.5   612.8    96.8     683    97.4
BR D #Mann= 3
       0     .06   434.7    .013   528.1     .06
BR D Banks=434.7,528.1
BC Design=,, 0 ,, 0 ,,,,,,
BC HTab HWMax=97.1
BC Use User HTab Curves=0
BC User HTab FreeFlow(D)= 0

Type RM Length L Ch R = 1 ,736.9327,343.5,367.8,385.2
BEGIN DESCRIPTION:
EHRA Add'l X-Sect (April 2011)
2001 Survey used for Overbanks
EHRA Survey Data used for Channel
END DESCRIPTION:
XS GIS Cut Line= 3
   3098006.6353413910755.5077207 3097928.450859713910549.3849999
 3097815.333479813910100.8845112
#Sta/Elev= 20
       0    93.7      90    93.1   187.5    93.4   285.5    93.2   412.3    92.5
   434.7    91.6   459.3    78.5   461.8    77.3   467.8    77.2   482.4    77.2
   497.3    77.3   503.2   77.26   504.4    78.4   528.1    91.5   553.2    93.3
   568.7    95.5     582    95.2   596.4    96.5   612.8    96.8     683    97.4
#Mann= 3 ,-1 , 0
       0     .06       0   434.7    .013       0   528.1     .06       0
#XS Ineff= 2 , 0
       0   461.5    94.3   503.2       0   95.17
Permanent Ineff=
       F       F
Bank Sta=434.7,528.1
XS Rating Curve= 0 ,0
Exp/Cntr=0.5,0.3

Type RM Length L Ch R = 1 ,369.1198,278.9,235.2,208.2
BEGIN DESCRIPTION:
EHRA Add'l X-Sect (April 2011)
2001 LiDAR used for Overbanks
EHRA Survey Data used for Channel
END DESCRIPTION:
XS GIS Cut Line= 4
 3098437.834594913910802.8922542 3098224.604194213910343.2622791
 3098226.9734208 13910132.401105 3098131.005427913910009.7753362
#Sta/Elev= 21
       0   93.55  290.81   95.36  441.13    94.4  505.41    93.5  506.68   93.51
  515.73   93.57   539.4    95.1   562.9    95.9   595.8    85.6   617.6    82.5
   622.2    77.9   623.9    77.5   627.1    77.5   630.7    80.7   644.6    89.3
   661.6    95.7   683.2      95   715.6      95  752.53   93.49  832.88   93.64
  873.27   93.89
#Mann= 3 , 0 , 0
       0     .15       0   562.9     .04       0   661.6     .15       0
Bank Sta=562.9,661.6
XS Rating Curve= 0 ,0
Exp/Cntr=0.3,0.1

Type RM Length L Ch R = 1 ,133.9   ,133.9,133.9,133.9
BEGIN DESCRIPTION:
11
END DESCRIPTION:
XS GIS Cut Line= 4
     3098939.958    13911006.028      3098719.37    13910642.328
     3098200.786    13909787.301      3097983.41    13909428.897
#Sta/Elev= 30
       0   90.89  103.58   89.67  254.42   90.96  326.04   90.44  463.18   92.02
  520.57   94.25  669.51   93.72  713.71    94.6  815.88   92.87  856.13   94.24
  887.35   94.05  907.29   79.53   919.3   76.24  927.28   75.68  932.46   79.04
  966.54   92.06  975.98   89.31  989.48   90.16 1052.69   89.61 1070.14   91.17
 1156.92   89.48 1208.09   91.03 1328.95   91.64 1431.83   91.32 1515.77   89.01
 1565.94   90.58  1634.2   90.71 1673.66   89.28 1778.92   88.48 1844.54   90.57
#Mann= 3 , 0 , 0
       0     .15       0  887.35     .04       0  966.54     .15       0
#XS Ineff= 2 , 0
       0  887.35      95  966.54       0      95
Permanent Ineff=
       T       T
Bank Sta=887.35,966.54
XS Rating Curve= 0 ,0
Exp/Cntr=0.3,0.1

Chan Stop Cuts=-1
Use User Specified Reach Order=0
Composite Channel Slope=5